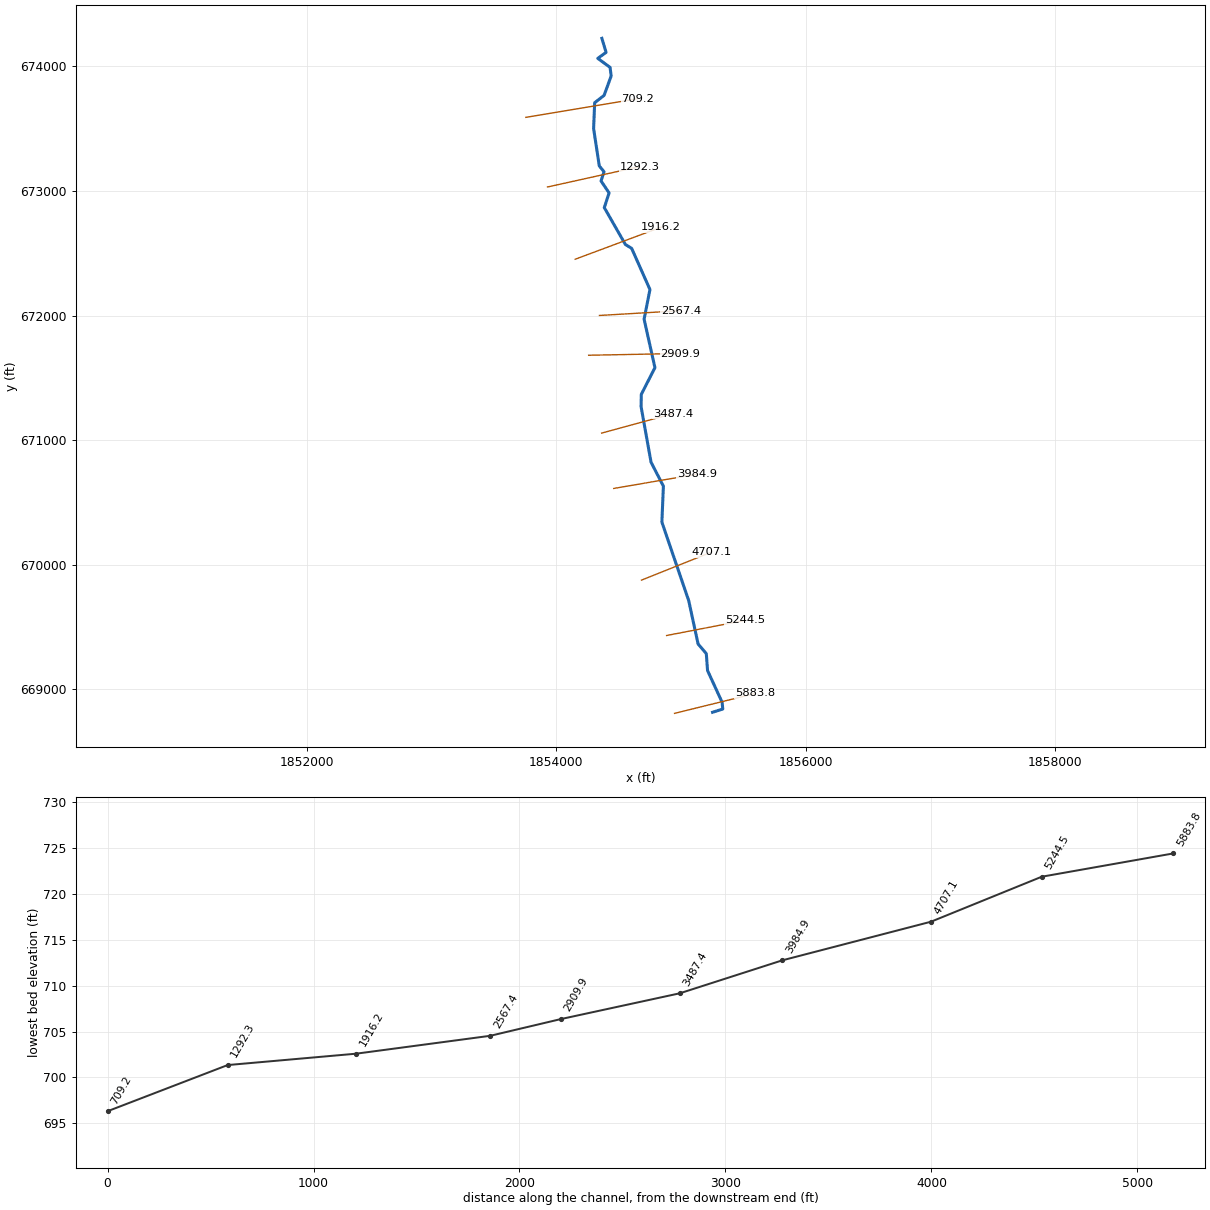
--- BearRun.prj (project) ---

Proj Title=BearRun
Current Plan=p01
Default Exp/Contr=0,0
English Units
Geom File=g01
Flow File=f01
Plan File=p01
BEGIN DESCRIPTION:
AMEC Environment & Infrastructure, 2013
Projection: NAD 1983 State Plane West Virginia South FIPS 4702 (US Feet)
Vertical Datum: NAVD 1988
END DESCRIPTION:
DSS Export Rating Curves= 0
DSS Export Rating Curve Sorted= 0
DSS Export Volume Flow Curves= 0
DXF OffsetX= 0
DXF OffsetY= 0
DXF ScaleX= 0
DXF ScaleY= 0

--- BearRun.p01 (plan) ---

Plan Title=Floodplain
Program Version=4.00
Geom File=g01
Flow File=f01
K Sum by GR=0
Std Step Tol=0.01
Critical Tol=0.01
Num of Std Step Trials=20
Max Error Tol=0.3
Flow Tol Ratio=0.001
Split Flow NTrial=30
Split Flow Tol=0.02
Split Flow Ratio=0.02
Log Output Level=0
Friction Slope Method=1
Unsteady Friction Slope Method=2
Unsteady Bridges Friction Slope Method=1
Global Log Level=0
CheckData=False
Run HTab=0
Run UNet=0
Run PostProcess=0
UNET Theta=0
UNET Theta Warmup=0
UNET ZTol=0
UNET ZSATol=0
UNET MxIter=0
UNET MaxInSteps=0
UNET DtIC=0
UNET DtMin=0
UNET MaxCRTS=0
UNET WFStab=0
UNET SFStab=0
UNET WFX=0
UNET SFX=0
UNET DSS MLevel=0
UNET DZMax Abort=0
UNET Convert EG Bridges=0
UNET Use Existing IB Tables=0
UNET Froude Limit=0
UNET Froude Power=0
Write IC File=0
Echo Input=False
Echo Output=False
Write Detailed=0

--- BearRun.f01 (steady flow) ---

Flow Title=NFF Regression Equation
Program Version=4.00
Number of Profiles=1
Profile Names=P100yr
River Rch & RM=BearRun,Main      ,5883.8
870.6299
River Rch & RM=BearRun,Main      ,5244.5
918.3981
River Rch & RM=BearRun,Main      ,4707.1
987.8857
River Rch & RM=BearRun,Main      ,3487.4
1082.475
Boundary for River Rch & Prof#=BearRun,Main      ,1
Up Type=0
Dn Type=3
Dn Slope=0.004562

--- BearRun.g01 (geometry) ---

Geom Title=USGS 3m DEM
Program Version=4.10

River Reach=BearRun         ,Main
Reach XY= 30
     1855253.761      668815.542     1855335.387      668841.598
     1855330.173      668895.438     1855213.468      669150.356
     1855203.366      669286.202     1855137.363      669364.352
     1855062.469      669711.279     1854847.263      670342.132
     1854859.402      670630.436     1854760.395      670823.211
     1854680.476      671269.554     1854682.235      671367.389
     1854791.609      671582.179     1854704.746      671971.209
     1854751.624      672209.149     1854604.697      672540.144
     1854554.896       672570.63     1854385.666       672867.01
     1854424.119      672984.821     1854359.651      673080.736
     1854383.243      673154.674     1854345.415      673201.911
     1854299.983      673501.275     1854308.376      673708.866
     1854384.123      673767.896     1854440.634      673923.319
     1854431.946      673992.789     1854333.415      674065.054
     1854400.081       674113.02      1854366.21      674225.903

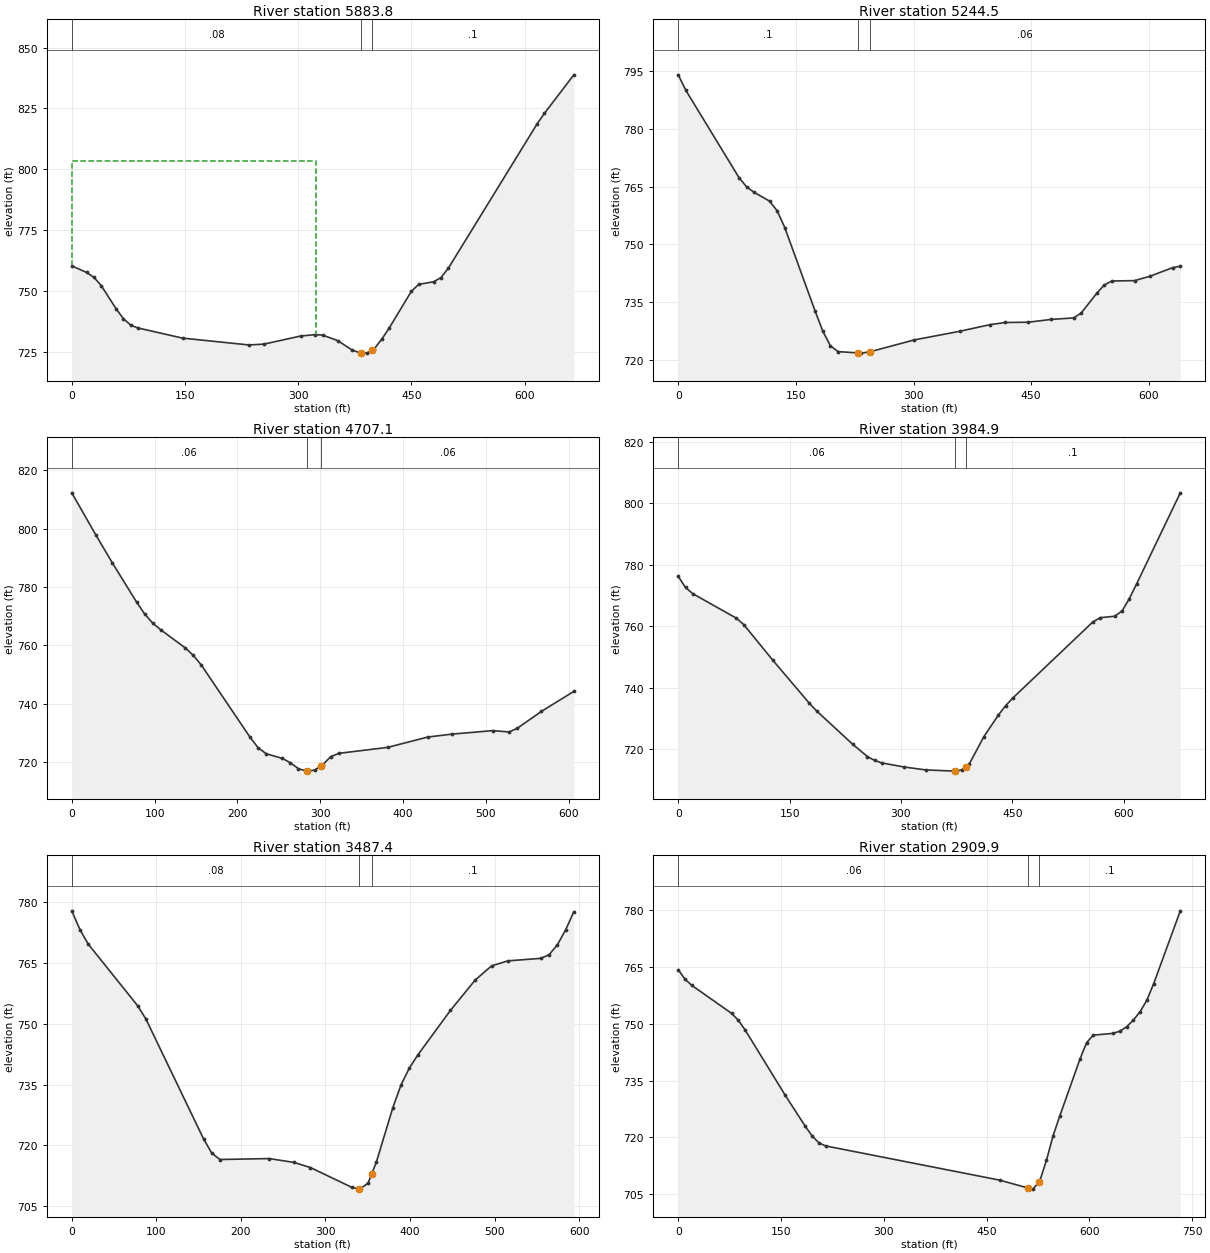
Type RM Length L Ch R = 1 ,5883.8  ,640.4,639.3,637
XS GIS Cut Line= 2
     1854948.883      668806.669     1855594.716      668966.392
#Sta/Elev= 30
       0  760.26    19.6  757.58    29.4  755.57    39.1  752.15    58.7  742.66
    68.5  738.53    78.3  735.88      88  734.73   146.8  730.58   234.8  727.77
   254.4   728.1   303.3  731.44   322.9  732.02   332.6   731.8   352.2  729.59
   371.8  725.61   383.1  724.45   391.4  724.41   398.1  725.72   401.1   726.3
   410.9  730.19   420.7  734.77     450  749.82   459.8  752.68   479.4  753.72
   489.2  755.46     499   759.3   616.4  818.52   626.2  822.91   665.3  838.79
#Mann= 3 , 0 , 0
       0     .08       0   383.1    .045       0   398.1      .1       0
#XS Ineff= 2 , 0
          323.65  803.57
Permanent Ineff=
       F       F
Bank Sta=383.1,398.1
XS Rating Curve= 0 ,0
Exp/Cntr=0.3,0.1

Type RM Length L Ch R = 1 ,5244.5  ,532.4,537.5,541.3
XS GIS Cut Line= 2
      1854885.16      669431.763     1855513.632      669553.291
#Sta/Elev= 30
       0  793.91     9.7  789.89    77.6  767.26    87.3  764.88      97  763.46
   116.4  761.22   126.1  758.72   135.8  754.38   174.6  732.71   184.3  727.57
     194  723.76   203.7  722.27     229  721.92   232.8  721.87     244   722.2
   300.7  725.28   358.8  727.52   397.6  729.25     417   729.8   446.1  729.87
   475.2  730.59   504.3  730.99     514  732.31   533.4  737.33   543.1  739.49
   552.8  740.54   581.9  740.64   601.3  741.77   630.4     744   640.1  744.36
#Mann= 3 , 0 , 0
       0      .1       0     229    .045       0     244     .06       0
Bank Sta=229,244
XS Rating Curve= 0 ,0
Exp/Cntr=0.3,0.1

Type RM Length L Ch R = 1 ,4707.1  ,727.8,722.1,715.8
XS GIS Cut Line= 2
     1854683.771      669876.208     1855246.271      670101.902
#Sta/Elev= 30
       0  812.28    29.3  797.74    48.9  788.32    78.2  774.89      88  770.79
    97.8  767.63   107.5  765.35   136.9   759.2   146.6  756.66   156.4   753.3
   215.1  728.63   224.8  725.04   234.6  722.94   254.2  721.33   263.9  719.83
   273.7   717.8   283.5  716.97   293.3  717.29   300.7  718.74     303  719.19
   312.8  721.96   322.6  723.07   381.2   725.1   430.1  728.66   459.4  729.66
   508.3  730.84   527.9  730.38   537.7  731.62     567  737.43   606.1  744.29
#Mann= 3 , 0 , 0
       0     .06       0   283.5    .045       0   300.7     .06       0
Bank Sta=283.5,300.7
XS Rating Curve= 0 ,0
Exp/Cntr=0.3,0.1

Type RM Length L Ch R = 1 ,3984.9  ,494.4,497.5,500.8
XS GIS Cut Line= 2
     1854461.549      670612.319     1855128.215      670726.902
#Sta/Elev= 30
       0  776.19     9.8  772.59    19.6  770.56    78.4  762.57    88.2  760.51
   127.4   748.9   176.5   734.9   186.3   732.4   235.3  721.45   254.9  717.51
   264.7  716.23   274.5  715.43   303.9  714.12   333.3  713.16   372.5  712.76
   372.7  712.77   382.3  713.16   387.7  714.22   392.1  715.09   411.8  724.01
   431.4  731.06   441.2  734.12     451  736.64   558.8  761.41   568.6  762.75
   588.2  763.22     598  764.97   607.8  768.99   617.6  773.79   676.4  803.42
#Mann= 3 , 0 , 0
       0     .06       0   372.7    .045       0   387.7      .1       0
Bank Sta=372.7,387.7
XS Rating Curve= 0 ,0
Exp/Cntr=0.3,0.1

Type RM Length L Ch R = 1 ,3487.4  ,584,577.6,568.7
XS GIS Cut Line= 2
     1854364.327      671056.763     1854937.243      671213.013
#Sta/Elev= 30
       0  777.94     9.7  773.29    19.5  769.71    77.9  754.49    87.6  751.24
   155.8  721.61   165.5  718.08   175.2  716.49   233.6  716.72   262.8  715.77
   282.3   714.5     331  709.63   339.8  709.21   340.7  709.17   350.5  710.68
   354.8  712.96   360.2  715.82   379.7  729.28   389.4  734.91   399.1  739.01
   408.9  742.22   447.8  753.32     477  760.81   496.5  764.34     516  765.58
   554.9   766.2   564.6  767.11   574.4  769.56   584.1  773.25   593.8  777.72
#Mann= 3 , 0 , 0
       0     .08       0   339.8    .045       0   354.8      .1       0
Bank Sta=339.8,354.8
XS Rating Curve= 0 ,0
Exp/Cntr=0.3,0.1

Type RM Length L Ch R = 1 ,2909.9  ,340.2,342.4,345.4
XS GIS Cut Line= 2
      1854260.16      671681.763     1854992.799      671695.652
#Sta/Elev= 30
       0  764.26     9.8   761.8    19.5  760.18    78.2  752.72    87.9  750.89
    97.7  748.36   156.3   731.1   185.6   722.9   195.4   720.4   205.2  718.59
     215  717.77     469  708.74   511.2  706.62   517.8  706.36   526.2  708.17
   527.6  708.47   537.4  713.95   547.1  720.45   556.9  725.68   586.2  740.62
     596  745.02   605.8  747.01   635.1  747.48   644.8  748.08   654.6  749.23
   664.4  751.02   674.2  753.22   683.9  756.21   693.7  760.48   732.8  779.82
#Mann= 3 , 0 , 0
       0     .06       0   511.2    .045       0   526.2      .1       0
Bank Sta=511.2,526.2
XS Rating Curve= 0 ,0
Exp/Cntr=0.3,0.1

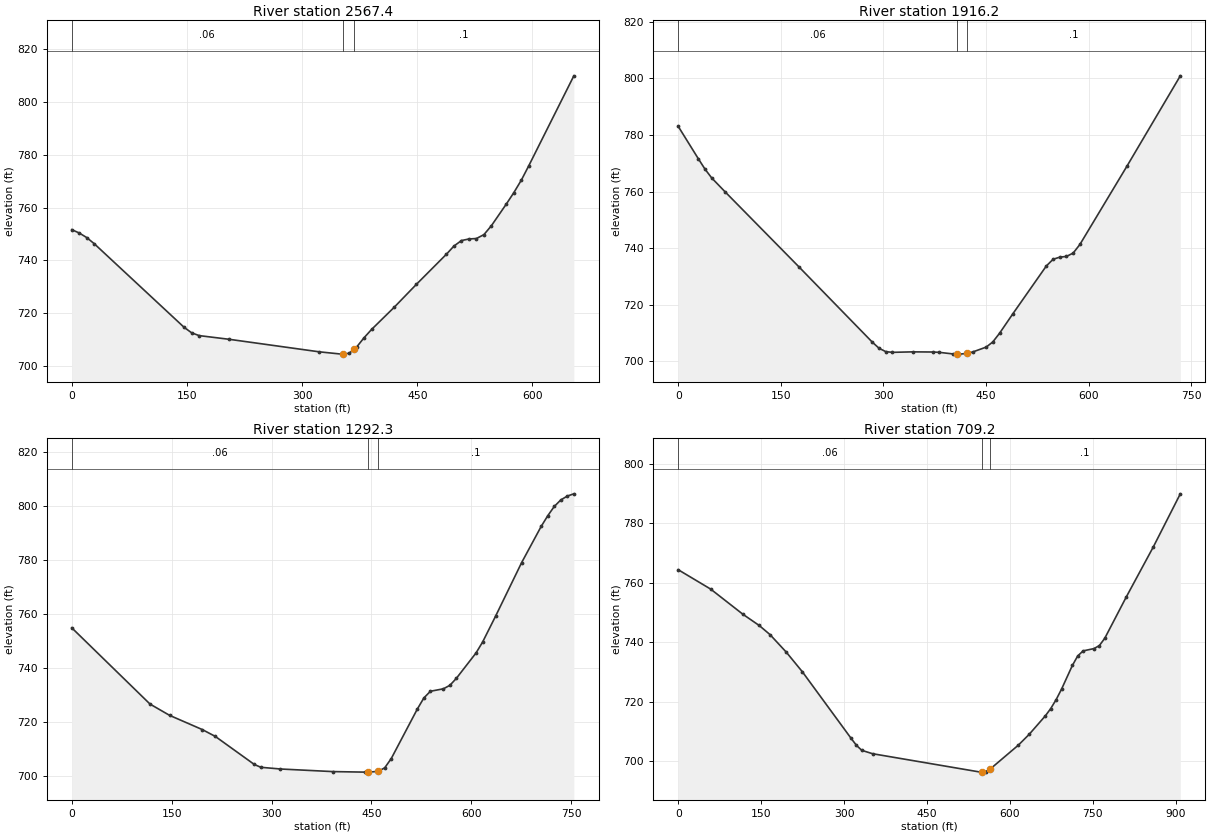
Type RM Length L Ch R = 1 ,2567.4  ,644.5,651.3,656.9
XS GIS Cut Line= 2
     1854346.965      672001.208     1854999.743      672039.402
#Sta/Elev= 30
       0  751.64     9.8  750.36    19.5  748.64    29.3  746.31   146.4  714.66
   156.2  712.59   165.9  711.55     205  710.15   322.1  705.42   351.4  704.54
   352.6  704.57   361.1  704.82   367.6  706.39   370.9  707.18   380.6  710.71
   390.4  713.86   419.7   722.2   448.9  730.96     488  742.36   497.7  745.42
   507.5  747.51   517.3  748.11     527  748.28   536.8  749.76   546.5  753.12
   566.1  761.39   575.8  765.67   585.6  770.42   595.3  775.87   653.9  809.84
#Mann= 3 , 0 , 0
       0     .06       0   352.6    .045       0   367.6      .1       0
Bank Sta=352.6,367.6
XS Rating Curve= 0 ,0
Exp/Cntr=0.3,0.1

Type RM Length L Ch R = 1 ,1916.2  ,613.1,623.9,621.8
XS GIS Cut Line= 2
     1854152.521      672452.597     1854840.021      672709.541
#Sta/Elev= 30
       0  782.99    29.4  771.56    39.1  767.91    48.9   764.8    68.5  759.89
   176.2  733.46   283.8   706.8   293.6  704.66   303.4  703.47   313.2  703.22
   342.5  703.39   371.9  703.34   381.6  703.22   401.2  702.67     407  702.62
     411  702.59     422  702.82   430.6  703.36   450.2  705.07   459.9   706.9
   469.7  709.94   489.3  716.87   538.2  733.73     548  736.07   557.8  736.83
   567.6  737.08   577.4  738.28   587.2   741.3   655.7  768.83     734  800.84
#Mann= 3 , 0 , 0
       0     .06       0     407    .045       0     422      .1       0
Bank Sta=407,422
XS Rating Curve= 0 ,0
Exp/Cntr=0.3,0.1

Type RM Length L Ch R = 1 ,1292.3  ,596.6,583.1,575.8
XS GIS Cut Line= 2
     1853930.299      673032.458      1854666.41      673195.652
#Sta/Elev= 30
       0  754.78   117.5  726.55   146.9  722.37   195.8  717.13   215.4   714.6
   274.2  704.18     284  703.14   313.3  702.51   391.7  701.55   440.6  701.35
     445  701.36     460  701.61     470  702.95   479.8  706.38     519  724.73
   528.8  728.82   538.6  731.29   558.1   732.2   567.9   733.5   577.7  736.12
   607.1  745.47   616.9  749.48   636.5  759.11   675.6  778.93     705  792.35
   714.8  796.27   724.6  799.71   734.4  802.13   744.2  803.56     754  804.39
#Mann= 3 , 0 , 0
       0     .06       0     445    .045       0     460      .1       0
Bank Sta=445,460
XS Rating Curve= 0 ,0
Exp/Cntr=0.3,0.1

Type RM Length L Ch R = 1 ,709.2   ,705.7,709.2,707.6
XS GIS Cut Line= 2
     1853756.688      673591.486     1854652.521      673740.791
#Sta/Elev= 30
       0  764.38    58.6  757.88   117.2  749.38   146.5  745.63     166  742.57
   195.3   736.7   224.6  730.05   312.5  707.73   322.3  705.34     332  703.65
   351.6  702.51   546.9  696.32   548.8  696.36   556.6  696.53   563.8  697.28
   615.2  705.39   634.8  709.02     664  715.23   673.8   717.7   683.6   720.7
   693.4  724.24   712.9  732.18   722.6  735.39   732.4  737.09   751.9  737.86
   761.7  738.86   771.5  741.32   810.5  755.24   859.4  772.07   908.2  789.91
#Mann= 3 , 0 , 0
       0     .06       0   548.8    .045       0   563.8      .1       0
Bank Sta=548.8,563.8
XS Rating Curve= 0 ,0
Exp/Cntr=0.3,0.1

Chan Stop Cuts=-1
Use User Specified Reach Order=0
Composite Channel Slope=5